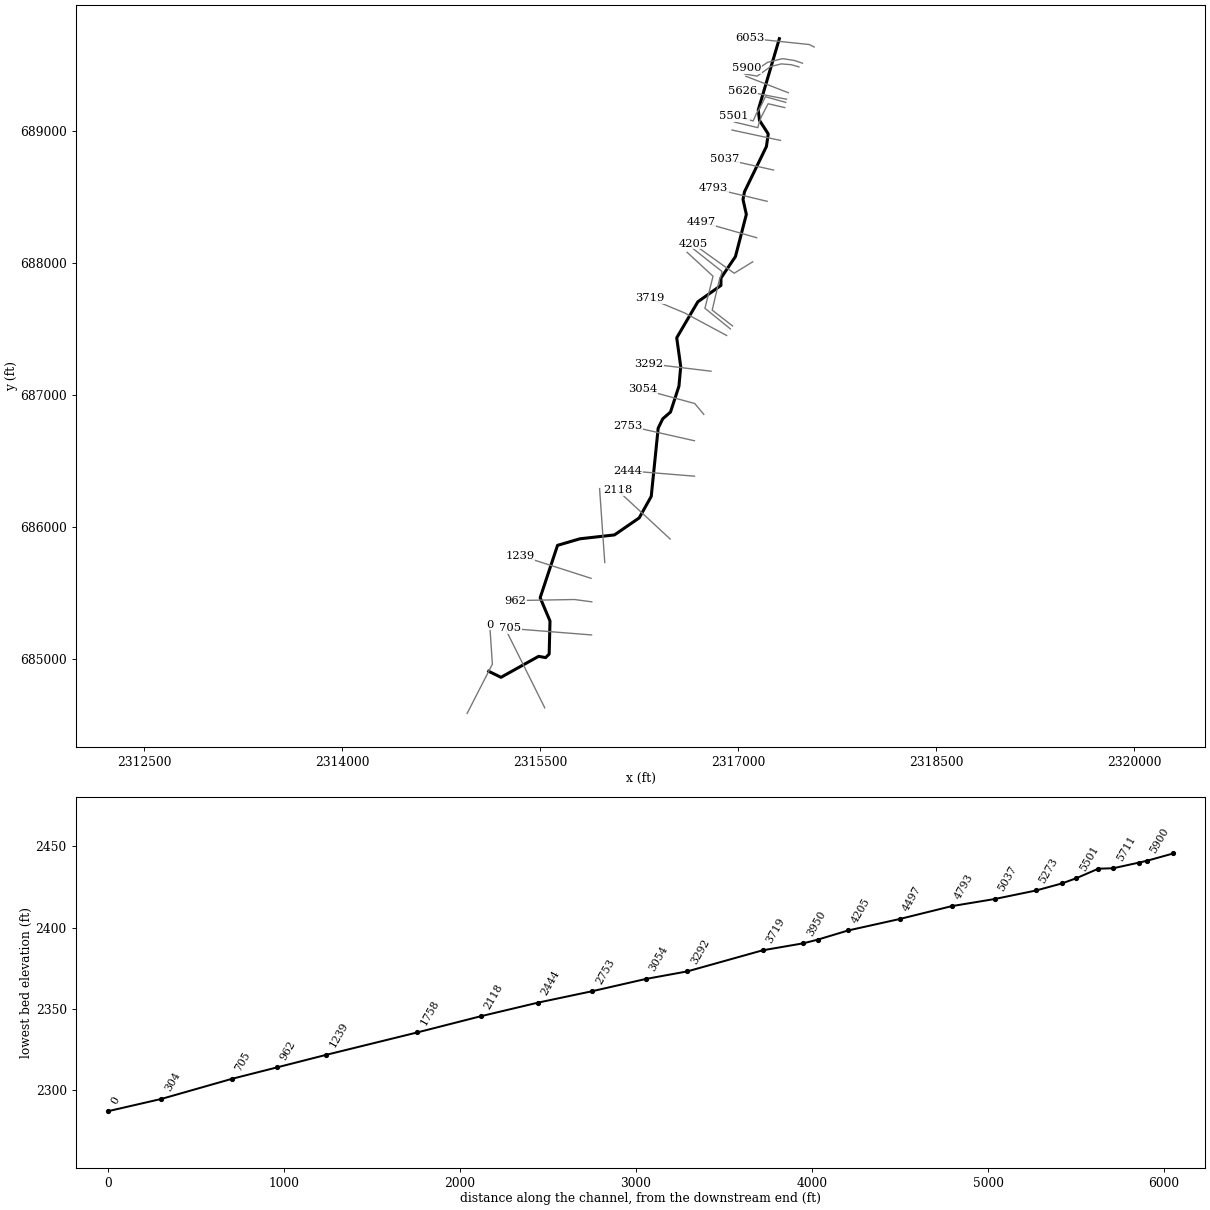
--- LFKCHENOCK.prj (project) ---

Proj Title=LFKCHENOCK
Current Plan=p01
Default Exp/Contr=0,0
English Units
Geom File=g01
Flow File=f01
Plan File=p01
BEGIN DESCRIPTION:
----------MODEL BY WSP USA 2022----------
AFH study
Randolph County, WV
HEC-RAS Version: RAS 6.2
Vertical Datum: NAVD88
Projection: NAD 1983 StatePlane West Virginia S FIPS 4702 (US Feet)
Terrain: 1-meter LIDAR (FEMA Region III 3DEP collected 2016-2018)
Land Use: 2019 NLCD
Hydrologic Method:
WV SIR2010-5033 regression equations
Additional Model Notes:
KWSE with Chenoweth Creek at DS boundary due to name change
END DESCRIPTION:
DSS Export Rating Curves= 0
DSS Export Rating Curve Sorted= 0
DSS Export Volume Flow Curves= 0
DXF OffsetX= 0
DXF OffsetY= 0
DXF ScaleX= 0
DXF ScaleY= 0

--- LFKCHENOCK.p01 (plan) ---

Plan Title=Floodplain
Program Version=6.20
Short Identifier=Floodplain
Geom File=g01
Flow File=f01
Subcritical Flow
K Sum by GR= 0
Std Step Tol= 0.01
Critical Tol= 0.01
Num of Std Step Trials= 20
Max Error Tol= 0.3
Flow Tol Ratio= 0.001
Split Flow NTrial= 30
Split Flow Tol= 0.02
Split Flow Ratio= 0.02
Log Output Level= 0
Friction Slope Method= 1
Unsteady Friction Slope Method= 2
Unsteady Bridges Friction Slope Method= 1
Parabolic Critical Depth
Global Vel Dist= 0 , 0 , 0
Global Log Level= 0
CheckData=True
Encroach Param=-1 ,0,0, 0
Mapping Interval=1HOUR
Computation Time Step Use Courant=        0
Computation Time Step Use Time Series=    0
Computation Time Step Count To Double=0
Computation Time Step Max Doubling=0
Computation Time Step Max Halving=0
Computation Time Step Residence Courant=0
Run HTab= 0
Run UNet= 0
Run Sediment= 0
Run PostProcess= 0
Run WQNet= 0
Run RASMapper=-1
UNET Theta= 0
UNET Theta Warmup= 0
UNET ZTol= 0
UNET ZSATol= 0
UNET MxIter= 0
UNET Max Iter WO Improvement= 0
UNET MaxInSteps= 0
UNET DtIC= 0
UNET DtMin= 0
UNET MaxCRTS= 0
UNET WFStab= 0
UNET SFStab= 0
UNET WFX= 1
UNET SFX= 1
UNET Gravity=32.174
UNET 1D Methodology=Finite Difference
UNET DSS MLevel= 1
UNET Pardiso=0
UNET DZMax Abort= 0
UNET Use Existing IB Tables= 0
UNET Froude Reduction=False
UNET Froude Limit= 0
UNET Froude Power= 0
UNET D1 Cores= 0
UNET WindReference=Eulerian
UNET WindDragFormulation=Hsu (1988)
UNET D2 Coriolis=0
UNET D2 Cores= 0
UNET D2 Theta= 1
UNET D2 Theta Warmup= 1
UNET D2 Z Tol= 0.01
UNET D2 Volume Tol= 0.01
UNET D2 Max Iterations= 20
UNET D2 Equation= 0
UNET D2 RampUpFraction=0.1
UNET D2 TimeSlices= 1
UNET D2 Turbulence Formulation=Non-Conservative (original)
UNET D2 Eddy Viscosity=0.3
UNET D2 Transverse Eddy Viscosity=0.1
UNET D2 Smagorinsky Mixing=0
UNET D2 BCVolumeCheck=0
UNET D2 Cores=0
UNET D2 SolverType=PARDISO (Direct)
UNET D2 Minimum Iterations= 2147483647
UNET D2 Maximum Iterations= 2147483647
UNET D2 Restart Number= 10
UNET D2 Relaxation Coeff=1.3
UNET D2 SOR Precondition Iterations= 10
UNET D2 ILUT Maximum Fill= 8
UNET D2 ILUT Tolerance=1E-08
UNET D1D2 MaxIter= 0
UNET D1D2 ZTol=0.01
UNET D1D2 QTol=0.1
UNET D1D2 MinQTol=1
Write IC File= 0
Write IC File at Fixed DateTime=0
Write IC File at Sim End=0
Echo Input=False
Echo Parameters=False
Echo Output=False
Write Detailed= 0
HDF Write Warmup=0
HDF Write Time Slices=0
HDF Flush=0
HDF Compression= 1
HDF Chunk Size= 1
HDF Spatial Parts= 1
HDF Use Max Rows=0
HDF Fixed Rows= 1
Calibration Method= 0
Calibration Iterations= 20
Calibration Max Change=0.05
Calibration Tolerance=0.2
Calibration Maximum=1.5
Calibration Minimum=0.5
Calibration Optimization Method= 1
WQ AD Non Conservative
WQ ULTIMATE=-1
WQ Max Comp Step=1HOUR
WQ Output Interval=15MIN
WQ Output Selected Increments= 0
WQ Output face flow=0
WQ Output face velocity=0
WQ Output face area=0
WQ Output face dispersion=0
WQ Output cell volume=0
WQ Output cell surface area=0
WQ Output cell continuity=0
WQ Output cumulative cell continuity=0
WQ Output face conc=0
WQ Output face dconc_dx=0
WQ Output face courant=0
WQ Output face peclet=0
WQ Output face adv mass=0
WQ Output face disp mass=0
WQ Output cell mass=0
WQ Output cell source sink temp=0
WQ Output nsm pathways=0
WQ Output nsm derived pathways=0
WQ Create Restart=0
WQ Fixed Restart=0
WQ System Summary=0
WQ Write To DSS=0
Sorting and Armoring Iterations= 10
XS Update Threshold= 0.02
Bed Roughness Predictor= 0
Hydraulics Update Threshold= 0.02
Energy Slope Method= 1
Volume Change Method= 1
Sediment Retention Method= 0
Sediment TS Multiplier= 1
Warm Up Method= 0
XS Weighting Method= 0
Number of US Weighted Cross Sections= 1
Number of DS Weighted Cross Sections= 1
Upstream XS Weight=0
Main XS Weight=1
Downstream XS Weight=0
Number of DS XS's Weighted with US Boundary= 1
Upstream Boundary Weight= 1
Weight of XSs Associated with US Boundary= 0
Number of US XS's Weighted with DS Boundary= 1
Downstream Boundary Weight= 0.5
Weight of XSs Associated with DS Boundary= 0.5
Percentile Method= 0
Sediment Output Level= 3
Mass or Volume Output= 0
Output Increment Type= 1
Profile and TS Output Increment= 1
Transport Output Increment 1
XS Output Flag= 0
XS Output Increment= 10
Read HDF5 Sediment Hotstart= 0
Sediment Hotstart Type= 0
Write Gradation File= 0
Read Gradation Hotstart= 0
Write HDF5 File= 1
Write Binary Output= 1
Write DSS Sediment File= 0
DSS Sediment Output Type= 1
SV Curve= 0
Specific Gage Flag= 0
Subcell Erosion Methods= 0
Subcell Deposition Methods= 0
Advection Scheme= 1
Matrix Solver= 0
Implicit Weighting Factor= 1
Maximum Outer Loop Convergence Iterations= 5
Convergence Maximum Absolute= 0.001
Convergence RMSE= 0.0001
Grain Fractions Max Abs Error= 0.001
Max Subgrid Regions= 1
Max Subgrid Length Scale= 3.402823E+38
Initial Layer Thickness= 3.402823E+38
Min Layer Thickness= 3.402823E+38
Max Layer Thickness= 3.402823E+38
Number of Layers= 5

--- LFKCHENOCK.f01 (steady flow) ---

Flow Title=Flow
Program Version=6.20
Number of Profiles= 1
Profile Names=P100yr
River Rch & RM=LFKCHENOCK,Main            ,6053
     557
River Rch & RM=LFKCHENOCK,Main            ,3292
     622
River Rch & RM=LFKCHENOCK,Main            ,2118
     712
River Rch & RM=LFKCHENOCK,Main            ,304
     846
River Rch & RM=LFKCHENOCK,Main            ,0
     968
Boundary for River Rch & Prof#=LFKCHENOCK,Main            , 1
Up Type= 0
Dn Type= 1
Dn Known WS=2290.8
DSS Import GetInterval= 0
DSS Import GetPeak= 0
DSS Import FillOption= 0

--- LFKCHENOCK.g01 (geometry) ---

Geom Title=Geometry
Program Version=6.20

River Reach=LFKCHENOCK      ,Main
Reach XY= 30
2317311.89300002689699.5390000052317152.01899999689159.521000013
     2317161.785689080.3110000192317227.82300003688978.094000012
     2317213.868688882.8290000112317047.85200003 688539.94600001
2317036.62899999688481.5960000162317061.95800002688368.505999997
     2316979.493 688049.49500002     2316869.675687886.644000009
2316869.38500004 687830.51000002     2316694.473687706.663000017
2316534.44599998687433.7730000172316564.83400004687216.880999997
2316551.45199999687067.9130000172316487.39000005686871.454999998
     2316428.543686820.0610000192316394.05500004686749.398000002
2316341.52891438686232.7174571812316250.47423674 686069.84864486
     2316063.067685940.8300000132315800.95500001685911.409000009
2315631.79800002685861.7960000192315500.12800001685465.180000007
2315574.59500001685288.8939999942315568.37700003685038.327000022
     2315541.502685011.261000007     2315488.457685021.059000015
2315203.40700004684862.1219999942315110.42520906684907.686550394

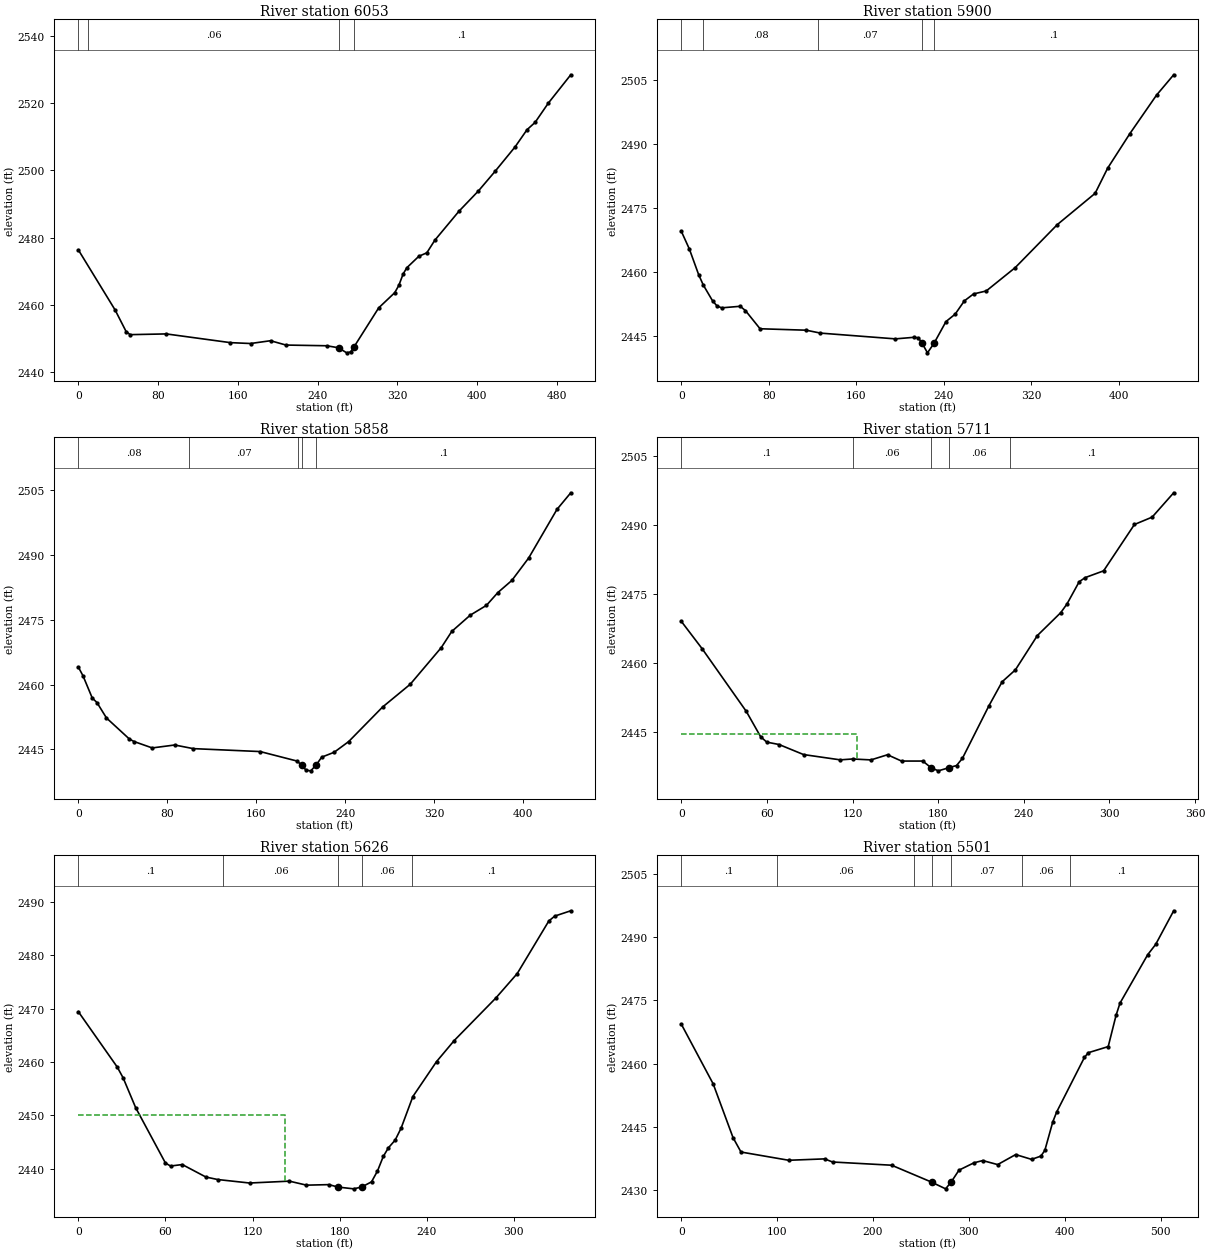
Type RM Length L Ch R = 1 ,6053    ,149.8,152.5,152.9
BEGIN DESCRIPTION:
Structure XS 4
END DESCRIPTION:
XS GIS Cut Line= 3
2317575.70053278689636.6733499962317538.22984671689655.408693031
2317088.58161388689702.247050618
#Sta/Elev= 30
       0 2476.31    36.9 2458.39      48 2451.93      52 2451.05    88.2 2451.27
   152.5 2448.67   172.7 2448.41   192.8 2449.24   208.3 2447.95   249.1 2447.74
     2612447.144   269.2 2445.63   273.2 2445.91  276.192447.239   301.3 2459.03
   317.4 2463.56   321.5 2465.73   325.8 2469.11   329.5 2470.98   341.6 2474.41
   349.6 2475.44   357.6 2479.18   381.8 2487.82   401.4 2493.89     418 2499.69
   438.1 2506.99   450.1 2512.12   458.2  2514.3   471.5 2520.05     494 2528.49
#Mann= 4 ,-1,0
       0      .1       0      10     .06       0     261    .045       0
  276.19      .1       0
Bank Sta=261,276.19
XS Rating Curve= 0 ,0
Exp/Cntr(USF)=0,0
Exp/Cntr=0.3,0.1

Type RM Length L Ch R = 1 ,5900    ,44.1,42.3,45.1
BEGIN DESCRIPTION:
Structure XS 3
END DESCRIPTION:
XS GIS Cut Line= 6
2317487.22807956 689513.85276788 2317425.8177885689534.669815696
2317336.30448289689548.2008967772317223.89242468689521.138734615
2317135.41997146689461.8101483392317064.64200889689474.300377029
#Sta/Elev= 30
       0 2469.54     7.4 2465.36    15.9 2459.35    20.1 2456.94    28.6 2453.23
    32.8 2451.99      37 2451.59    53.9 2451.95    58.7 2450.93      72 2446.69
   114.2 2446.35   127.2 2445.67   195.7 2444.32   212.4 2444.68   216.6 2444.57
   220.2 2443.25     225 2441.05  230.922443.256   241.9 2448.37   250.3 2450.11
   258.7 2453.22   267.1 2454.84   278.7 2455.54   305.2 2461.01   343.7 2471.09
   378.2  2478.4   389.6 2484.27   409.9 2492.36   434.3 2501.39     450 2506.16
#Mann= 5 ,-1,0
       0     .06       0      20     .08       0  124.84     .07       0
   220.2    .045       0  230.92      .1       0
Bank Sta=220.2,230.92
XS Rating Curve= 0 ,0
Exp/Cntr(USF)=0,0
Exp/Cntr=0.3,0.1

Type RM Length L Ch R = 1 ,5858    ,149.8,147.2,141.6
BEGIN DESCRIPTION:
Structure XS 2
END DESCRIPTION:
XS GIS Cut Line= 6
 2317460.1659174689485.749753327 2317402.9190359689502.403391581
2317326.93681138689508.6485059252317246.79117728  689488.8723105
2317143.74679059689416.0126431432317047.98837064689432.666281396
#Sta/Elev= 30
       0 2464.06     4.2 2462.03    12.5 2456.89    16.7 2455.85    25.3 2452.26
    45.8  2447.4      50 2446.81    66.4 2445.32    86.6    2446   103.3 2445.16
   163.4 2444.48   196.4 2442.29   200.6 2441.37   204.7 2440.15   208.9 2440.01
   213.8 2441.38   218.7 2443.18   229.9 2444.31     243  2446.8   273.4 2454.79
   298.3 2460.08   326.2 2468.58   335.6 2472.32   352.2 2476.09   366.8 2478.37
   377.1 2481.35   389.6 2484.14   404.8 2489.37   430.2 2500.62   442.6 2504.47
#Mann= 5 ,-1,0
       0     .08       0   99.62     .07       0   197.5      .1       0
   200.6    .045       0   213.8      .1       0
Bank Sta=200.6,213.8
XS Rating Curve= 0 ,0
Exp/Cntr(USF)=0,0
Exp/Cntr=0.3,0.1

Type RM Length L Ch R = 1 ,5711    ,83,84.8,85.9
BEGIN DESCRIPTION:
Structure XS 1
END DESCRIPTION:
XS GIS Cut Line= 2
2317380.02028331689290.0695038542317058.39689454689414.971790752
#Sta/Elev= 30
       0 2469.07    14.6 2463.11    45.6 2449.44    55.6 2443.95    59.9 2442.77
    68.5 2442.25    85.7 2440.06   111.4 2438.91     120  2439.1   132.9  2438.9
   144.5 2440.02   154.3 2438.65   169.2 2438.65  175.042437.192   180.1 2436.52
   187.7 2437.22   192.9 2437.68     197 2439.25   215.5 2450.65   224.8  2455.9
   234.1  2458.5   249.5 2465.97   265.9 2470.96   270.2 2472.82   278.8 2477.68
     283 2478.58   295.9 2480.05   317.5 2490.14   329.9 2491.74     345 2497.04
#Mann= 5 ,-1,0
       0      .1       0     120     .06       0  175.04    .045       0
   187.7     .06       0     230      .1       0
#XS Ineff= 2 , 0
          123.21 2444.55
Permanent Ineff=
       F       F
Bank Sta=175.04,187.7
XS Rating Curve= 0 ,0
Exp/Cntr(USF)=0,0
Exp/Cntr=0.3,0.1

Type RM Length L Ch R = 1 ,5626    ,110.9,125.2,129.5
BEGIN DESCRIPTION:
Structure XS 4
END DESCRIPTION:
XS GIS Cut Line= 2
2317366.48920223689241.1494414852317033.41643716689305.682289716
#Sta/Elev= 30
       0 2469.41    26.8 2459.04    30.9 2456.99    39.5 2451.43      60 2441.07
    63.5  2440.5    71.6 2440.78    87.9 2438.44    96.1 2437.97     118 2437.32
   145.4 2437.67   157.2 2436.92   172.7 2437.02   178.82436.566   189.7 2436.23
  195.232436.573     202 2437.54   206.1 2439.56   210.1 2442.29   213.6  2443.9
   218.3 2445.36   222.4  2447.6   230.5 2453.52   246.8 2460.06     259 2464.01
   287.6 2471.95   302.4 2476.55   324.2 2486.41   328.3 2487.32   339.3 2488.31
#Mann= 5 ,-1,0
       0      .1       0     100     .06       0   178.8    .045       0
  195.23     .06       0     230      .1       0
#XS Ineff= 2 , 0
          142.27 2450.07
Permanent Ineff=
       F       F
Bank Sta=178.8,195.23
XS Rating Curve= 0 ,0
Exp/Cntr(USF)=0,0
Exp/Cntr=0.3,0.1

Type RM Length L Ch R = 1 ,5501    ,80.5,81.7,90.8
BEGIN DESCRIPTION:
Structure XS 3
END DESCRIPTION:
XS GIS Cut Line= 6
2317360.24408788689217.2098364962317206.19793404 689259.88478452
2317169.76810036689184.9434123812317137.50167625689131.859940449
2317113.56207126689076.6947637362316969.92444132689113.124597414
#Sta/Elev= 30
       0 2469.37    33.3 2455.21      54  2442.5    62.3 2439.09   112.1 2437.14
   149.5 2437.47   157.8 2436.73   219.4 2435.97   261.6 2431.92   261.6 2431.91
   275.7 2430.38  281.482431.987   289.7 2434.81   305.3 2436.54   314.4 2437.07
     330 2436.12   348.8 2438.49   365.4 2437.35   375.1 2438.13   379.2 2439.48
   387.5 2446.23   391.6 2448.59   420.5 2461.48   424.6  2462.6   445.3 2464.04
   453.5 2471.45   457.6 2474.33   486.5 2485.79   494.8 2488.22   513.6 2496.18
#Mann= 7 ,-1,0
       0      .1       0     100     .06       0  243.17     .07       0
   261.6    .045       0  281.48     .07       0   355.3     .06       0
  405.43      .1       0
Bank Sta=261.6,281.48
XS Rating Curve= 0 ,0
Exp/Cntr(USF)=0,0
Exp/Cntr=0.3,0.1

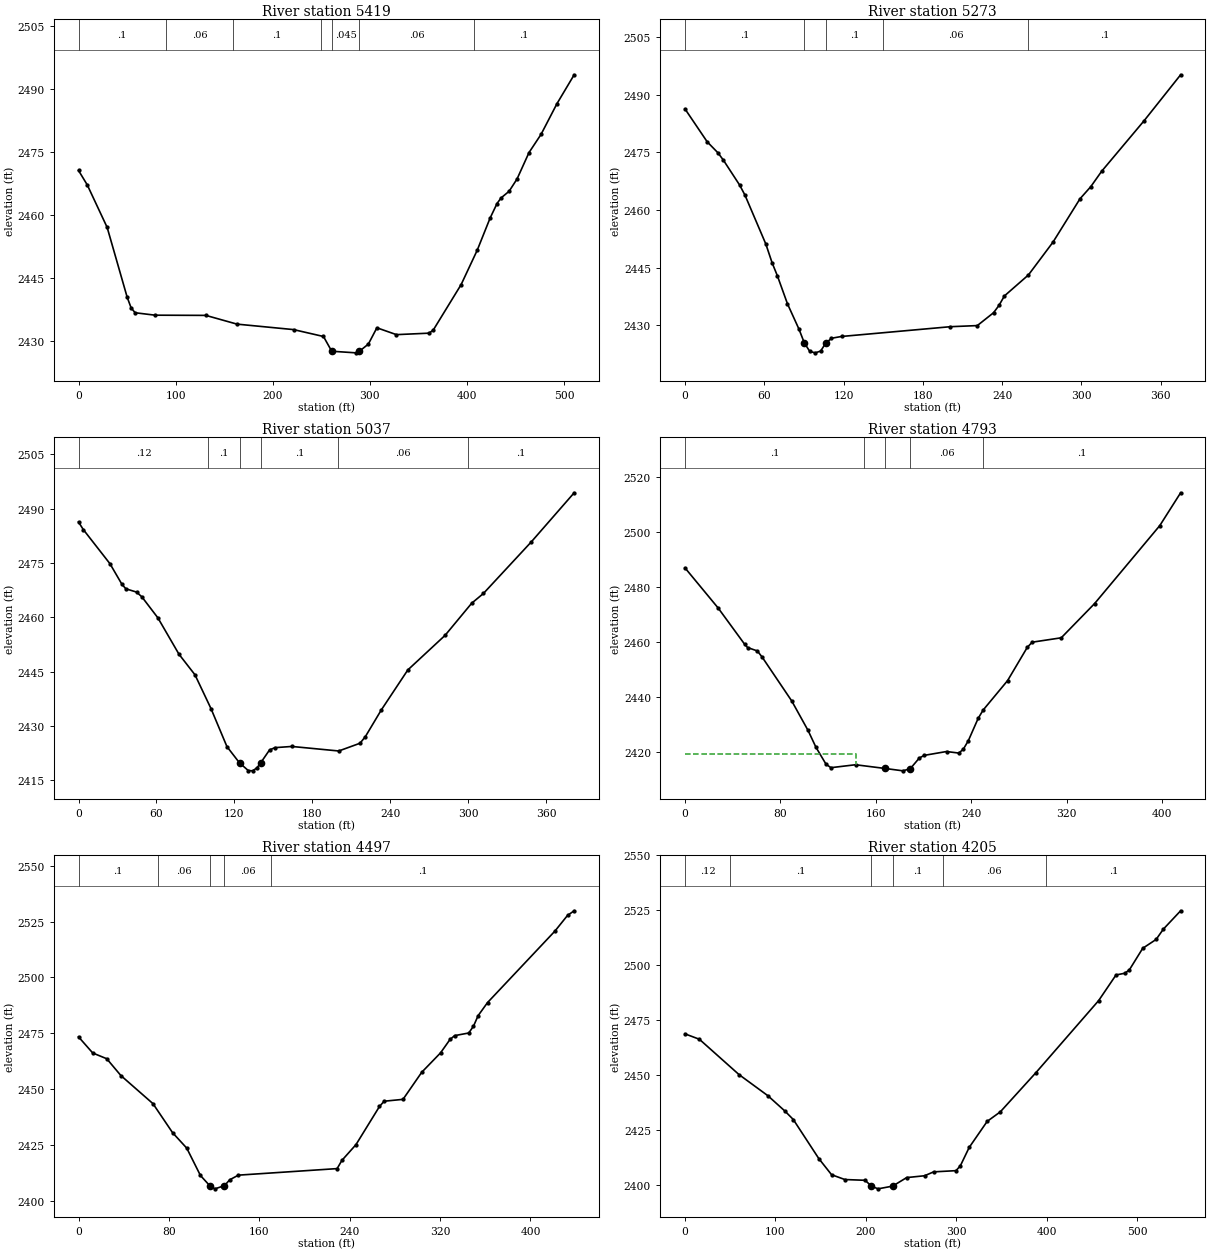
Type RM Length L Ch R = 1 ,5419    ,160.4,146.6,130.1
BEGIN DESCRIPTION:
Structure XS 2
END DESCRIPTION:
XS GIS Cut Line= 6
2317352.95812115689177.6574456452317227.01498186689206.801312588
2317176.01321471689108.9611878512317157.27787167689057.959420701
2317148.95105255689025.6929965862316970.96529371689068.367944609
#Sta/Elev= 30
       0 2470.57       9 2467.13    29.5 2457.01    50.1  2440.4    54.2 2437.85
    58.3 2436.71    78.8 2436.13   131.1 2436.08   163.2    2434   221.4  2432.7
   252.2 2431.06   260.7 2427.55   285.6 2427.17   289.2 2427.55   298.4 2429.25
   307.2 2433.13   327.3  2431.5   360.7 2431.85   365.1 2432.54   393.9  2443.4
   410.5 2451.59   423.7 2459.21   430.9  2462.7     435 2464.02   443.3 2465.61
   451.5 2468.54   463.8 2474.82   476.2 2479.15   492.6 2486.46   510.3 2493.33
#Mann= 7 ,-1,0
       0      .1       0      90     .06       0  159.27      .1       0
  249.65     .07       0   260.7    .045       0   289.2     .06       0
   407.3      .1       0
Bank Sta=260.7,289.2
XS Rating Curve= 0 ,0
Exp/Cntr(USF)=0,0
Exp/Cntr=0.3,0.1

Type RM Length L Ch R = 1 ,5273    ,235,235.3,235
BEGIN DESCRIPTION:
Structure XS 1
END DESCRIPTION:
XS GIS Cut Line= 2
2317320.60174682688928.9408410142316953.66201508689007.468799169
#Sta/Elev= 30
       0  2486.3    16.8 2477.75      25 2474.86    29.1 2472.96    41.3 2466.53
    45.4 2463.88    61.2 2451.15    65.9 2446.32      70 2442.83    77.6 2435.58
    86.3    2429    90.4 2425.38    94.5  2423.2    98.6 2422.84   102.7  2423.3
  106.41  2425.3   110.9 2426.63   118.5  2427.1   200.9 2429.64   221.3 2429.93
   233.6 2433.28   237.7 2435.18   241.8 2437.64     260 2443.11   278.6 2451.65
     299 2462.91   307.2 2466.08   315.4 2470.07   347.6 2483.25   375.2 2495.18
#Mann= 5 ,-1,0
       0      .1       0    90.4    .045       0  106.41      .1       0
     150     .06       0     260      .1       0
Bank Sta=90.4,106.41
XS Rating Curve= 0 ,0
Exp/Cntr(USF)=0,0
Exp/Cntr=0.3,0.1

Type RM Length L Ch R = 1 ,5037    ,243,244.1,243.6
XS GIS Cut Line= 2
 2317267.7738477688704.7792150082316895.12299173688787.590516335
#Sta/Elev= 30
       0 2486.28     3.7 2484.19    24.2 2474.78    33.5 2469.05    36.5 2467.84
    44.7 2466.94    48.8 2465.62    61.1 2459.84    77.4 2449.77    89.7  2444.1
     102  2434.8   114.3 2424.29     124 2419.79   130.7 2417.69   134.1  2417.6
   137.5 2418.46  140.192419.756   147.1 2423.36   151.2    2424   164.3 2424.33
   200.4 2423.08   216.8 2425.22   220.9 2427.04   233.2 2434.42   253.6 2445.45
   282.3    2455   302.8 2463.87   311.8 2466.55   348.7  2480.8   381.7 2494.35
#Mann= 6 ,-1,0
       0     .12       0     100      .1       0     124    .045       0
  140.19      .1       0     200     .06       0     300      .1       0
Bank Sta=124,140.19
XS Rating Curve= 0 ,0
Exp/Cntr(USF)=0,0
Exp/Cntr=0.3,0.1

Type RM Length L Ch R = 1 ,4793    ,294.2,296.4,295.2
XS GIS Cut Line= 2
2317219.22929175688467.7675594852316815.16725252688564.856671386
#Sta/Elev= 30
       0 2487.09    27.8 2472.49    50.1 2459.25    52.5  2458.1    60.7 2456.85
    64.8 2454.56    89.5 2438.66   103.2 2427.92   109.8 2421.82   118.3 2415.61
   122.4 2414.37     143 2415.44   167.7 2414.09   182.8 2413.22  188.96 2414.03
   196.5 2417.89   200.6 2418.85   219.3 2420.25   229.7 2419.68   233.5 2421.18
   237.6  2424.2   245.8 2432.29     250 2435.34   270.5 2446.06     287 2458.15
   291.1 2460.04   315.5 2461.64   343.4 2474.07   398.1 2502.46   415.6 2514.42
#Mann= 5 ,-1,0
       0      .1       0     150     .06       0   167.7    .045       0
  188.96     .06       0     250      .1       0
#XS Ineff= 2 , 0
          143.37 2419.48
Permanent Ineff=
       F       F
Bank Sta=167.7,188.96
XS Rating Curve= 0 ,0
Exp/Cntr(USF)=0,0
Exp/Cntr=0.3,0.1

Type RM Length L Ch R = 1 ,4497    ,294.3,291.5,286.7
XS GIS Cut Line= 2
2317140.25537747688191.8145498732316718.52401093688312.467355523
#Sta/Elev= 30
       0 2473.35    12.6 2466.12      25 2463.55    37.5 2456.02    65.9 2443.44
    83.3 2430.41    95.8 2423.52   107.9 2411.28  116.14 2406.71   120.7 2405.29
   129.2 2406.72   133.8 2409.33   141.5 2411.42   228.9 2414.35   233.1 2418.01
   245.6  2425.1   266.4 2442.18   270.5 2444.53   287.2 2445.36   303.8  2457.5
   320.4 2466.16   328.8 2472.17   332.9  2473.9   345.4 2475.08   349.6 2478.15
   353.7 2482.85     362 2488.69   421.7 2520.73   432.8 2527.72   438.7 2529.81
#Mann= 5 ,-1,0
       0      .1       0      70     .06       0  116.14    .045       0
   129.2     .06       0     170      .1       0
Bank Sta=116.14,129.2
XS Rating Curve= 0 ,0
Exp/Cntr(USF)=0,0
Exp/Cntr=0.3,0.1

Type RM Length L Ch R = 1 ,4205    ,191.6,173.2,163.7
BEGIN DESCRIPTION:
Structure XS 4
END DESCRIPTION:
XS GIS Cut Line= 4
2317110.05223759688009.5080471582316969.93947503687922.987181286
2316852.28837835688006.6501833662316658.11803835688145.591876725
#Sta/Elev= 30
       0 2468.78    15.9 2466.33    59.7 2450.26    91.5 2440.68   110.3 2433.72
   119.7 2429.82   147.9 2412.05     162 2404.71   176.7 2402.51   199.1 2402.17
   206.1 2399.49   213.4 2398.28  229.51 2399.52     245  2403.4   264.8 2404.23
   274.8    2406   299.5 2406.55   304.3 2408.72   314.1 2417.11     334 2428.97
   348.5  2433.3   387.9 2451.15   457.2 2483.92   476.4 2495.58   486.2 2496.36
   491.2 2497.93   505.9  2507.7   520.7 2511.73   528.8 2516.46   547.8 2524.77
#Mann= 6 ,-1,0
       0     .12       0      50      .1       0   206.1    .045       0
  229.51      .1       0  284.67     .06       0  399.04      .1       0
Bank Sta=206.1,229.51
XS Rating Curve= 0 ,0
Exp/Cntr(USF)=0,0
Exp/Cntr=0.3,0.1

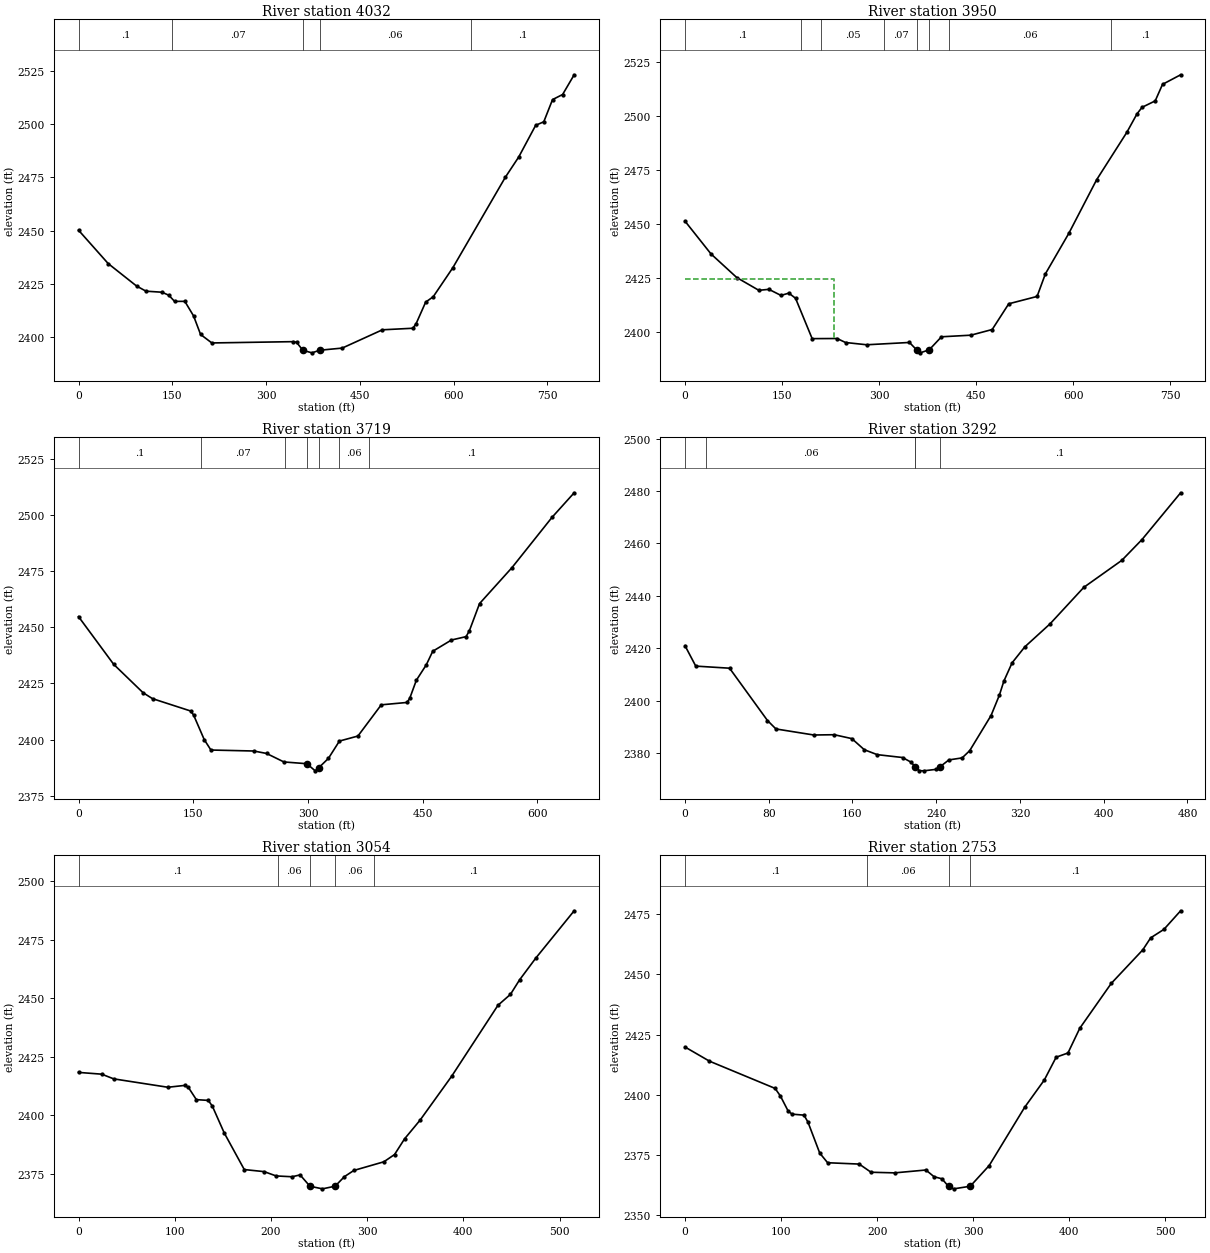
Type RM Length L Ch R = 1 ,4032    ,76.6,81.8,81.8
BEGIN DESCRIPTION:
Structure XS 3
END DESCRIPTION:
XS GIS Cut Line= 6
2316957.39857507687523.6885493462316803.28337719687643.729292012
 2316857.1571055687872.2929369132316872.33273336687911.749569344
2316877.58221621687936.3281240352316645.68048428688119.287732073
#Sta/Elev= 30
       0 2450.19    47.5 2434.51    92.8    2424     108 2421.56   133.4 2421.08
   144.4 2419.68   153.7 2416.78   170.1 2416.79   184.1 2409.95   195.3 2401.26
   213.3 2397.27   343.6 2397.88   348.9 2397.58   358.92393.821   373.5 2392.63
   385.82393.851   421.9 2394.86   486.2 2403.44     535 2404.17   540.1 2406.29
   555.4 2416.43   567.5 2418.95   598.9 2432.58   682.8 2474.99   704.3 2484.53
   731.4 2499.39   744.4 2501.06   758.4 2511.46   774.5 2513.85     793 2523.11
#Mann= 5 ,-1,0
       0      .1       0     150     .07       0   358.9    .045       0
   385.8     .06       0  627.58      .1       0
Bank Sta=358.9,385.8
XS Rating Curve= 0 ,0
Exp/Cntr(USF)=0,0
Exp/Cntr=0.3,0.1

Type RM Length L Ch R = 1 ,3950    ,218,231.4,238.8
BEGIN DESCRIPTION:
Structure XS 2
END DESCRIPTION:
XS GIS Cut Line= 4
2316941.04680184687501.3365256692316748.05099581687657.453734578
2316809.70234267687900.170189742 2316613.1126046688081.653246635
#Sta/Elev= 30
       0 2451.42    40.3 2436.19    80.1 2425.26   114.2 2419.35   129.7 2419.81
   148.4 2416.99   160.6 2418.05   170.9 2415.67   196.6 2396.96   235.1 2397.02
   248.2 2395.17   280.9 2394.12     347 2395.19   358.12391.759   363.5 2390.38
   377.5 2391.77   396.5 2397.82   441.9 2398.56   474.9 2401.19   500.5 2413.11
   544.3 2416.52   557.1 2426.97   593.3 2445.72   636.3 2470.57     683 2492.55
   698.6 2501.05   706.5 2504.15   726.9 2507.14   738.2  2514.8   766.2 2519.24
#Mann= 8 ,-1,0
       0      .1       0     180     .07       0     210     .05       0
  308.23     .07       0   358.1    .045       0   377.5     .07       0
  408.23     .06       0  658.66      .1       0
#XS Ineff= 2 , 0
           229.6 2424.41
Permanent Ineff=
       F       F
Bank Sta=358.1,377.5
XS Rating Curve= 0 ,0
Exp/Cntr(USF)=0,0
Exp/Cntr=0.3,0.1

Type RM Length L Ch R = 1 ,3719    ,423.4,427.3,429.7
BEGIN DESCRIPTION:
Structure XS 1
END DESCRIPTION:
XS GIS Cut Line= 3
2316912.72027441687451.3828806032316595.76415255687621.589706777
2316329.68190257687732.468334597
#Sta/Elev= 30
       0 2454.76      46  2433.5    84.4 2420.86    96.8 2418.21   146.5 2412.73
   150.4 2410.97   164.4 2399.95   173.1 2395.34   229.2  2394.9   245.8 2393.82
   268.5 2390.03   298.62389.242   309.4 2386.07   314.12387.463   326.7 2391.61
   341.1 2399.33   365.3 2401.57   395.8 2415.47   429.5 2416.53     433 2418.34
   441.7 2426.43   454.7  2433.3   463.1 2439.32   487.6 2444.34   506.7 2445.84
     511 2448.46   524.3 2460.56   566.7 2476.58   619.1 2498.99     648 2509.91
#Mann= 7 ,-1,0
       0      .1       0     160     .07       0     270      .1       0
   298.6    .045       0   314.1      .1       0     340     .06       0
  379.77      .1       0
Bank Sta=298.6,314.1
XS Rating Curve= 0 ,0
Exp/Cntr(USF)=0,0
Exp/Cntr=0.3,0.1

Type RM Length L Ch R = 1 ,3292    ,239,237.3,235.3
XS GIS Cut Line= 2
2316794.42674875687180.8090948152316324.37537184687237.606969525
#Sta/Elev= 30
       0 2420.96    10.3 2413.14    42.6 2412.34    78.8 2392.36    86.9 2389.13
   123.1 2386.82   142.6 2386.93   159.4 2385.44   171.3  2381.2   183.6 2379.32
   207.8 2378.22   215.8 2376.48  220.182374.604   223.9  2373.2   227.9 2373.13
     240  2373.7   243.2 2374.55   252.1  2377.3   264.8 2378.08     272 2380.84
   292.4 2394.27   300.4  2402.1   304.6 2407.38   312.5  2414.4   324.6 2420.48
   348.8  2429.3     381 2443.23   417.3 2453.54   436.6 2461.49   473.5 2479.36
#Mann= 5 ,-1,0
       0      .1       0      20     .06       0     220      .1       0
  220.18    .045       0   243.2      .1       0
Bank Sta=220.18,243.2
XS Rating Curve= 0 ,0
Exp/Cntr(USF)=0,0
Exp/Cntr=0.3,0.1

Type RM Length L Ch R = 1 ,3054    ,299.9,301.7,299.9
XS GIS Cut Line= 3
2316739.58742145686853.7316783822316671.03826232686935.990669341
2316277.37023415687043.710776549
#Sta/Elev= 30
       0 2418.26    24.1  2417.5    36.6 2415.49    92.9  2411.9   110.4 2412.69
   114.2 2411.84   122.5  2406.6   134.9 2406.28   139.1 2403.84   151.5 2392.33
   172.3 2376.69     193  2375.8   205.4 2373.96     222 2373.61   230.3  2374.4
   240.6 2369.54   253.6 2368.44   266.7 2369.57   276.4 2373.66   286.2 2376.31
   317.4 2380.01   328.5 2383.12   338.9 2389.82     355 2397.81   387.9 2416.64
     436 2446.98     449 2451.66   458.4 2457.82   475.3 2467.16   515.2 2487.41
#Mann= 5 ,-1,0
       0      .1       0  207.08     .06       0   240.6    .045       0
   266.7     .06       0  307.08      .1       0
Bank Sta=240.6,266.7
XS Rating Curve= 0 ,0
Exp/Cntr(USF)=0,0
Exp/Cntr=0.3,0.1

Type RM Length L Ch R = 1 ,2753    ,306.3,308.6,309.7
XS GIS Cut Line= 2
2316669.07971491686653.9598431952316165.73303214686767.555592615
#Sta/Elev= 30
       0 2419.88    25.5 2413.99    93.8 2402.69    99.3 2399.56   107.5 2393.21
   111.6 2391.99   123.9 2391.58     128 2388.72   140.3 2375.82   148.5 2371.82
   181.4 2371.26   193.7 2367.87   218.3 2367.61   250.8  2368.8   259.3 2366.01
   267.5 2365.15   274.4 2361.98   279.8 2360.98  296.972362.059   316.7 2370.65
   353.6 2394.83   374.1 2406.18   386.4 2415.64   398.7 2417.39     411 2427.65
   443.8  2446.3   476.6 2460.21   484.8  2465.2   498.6 2468.72     516 2476.44
#Mann= 4 ,-1,0
       0      .1       0     190     .06       0   274.4    .045       0
  296.97      .1       0
Bank Sta=274.4,296.97
XS Rating Curve= 0 ,0
Exp/Cntr(USF)=0,0
Exp/Cntr=0.3,0.1

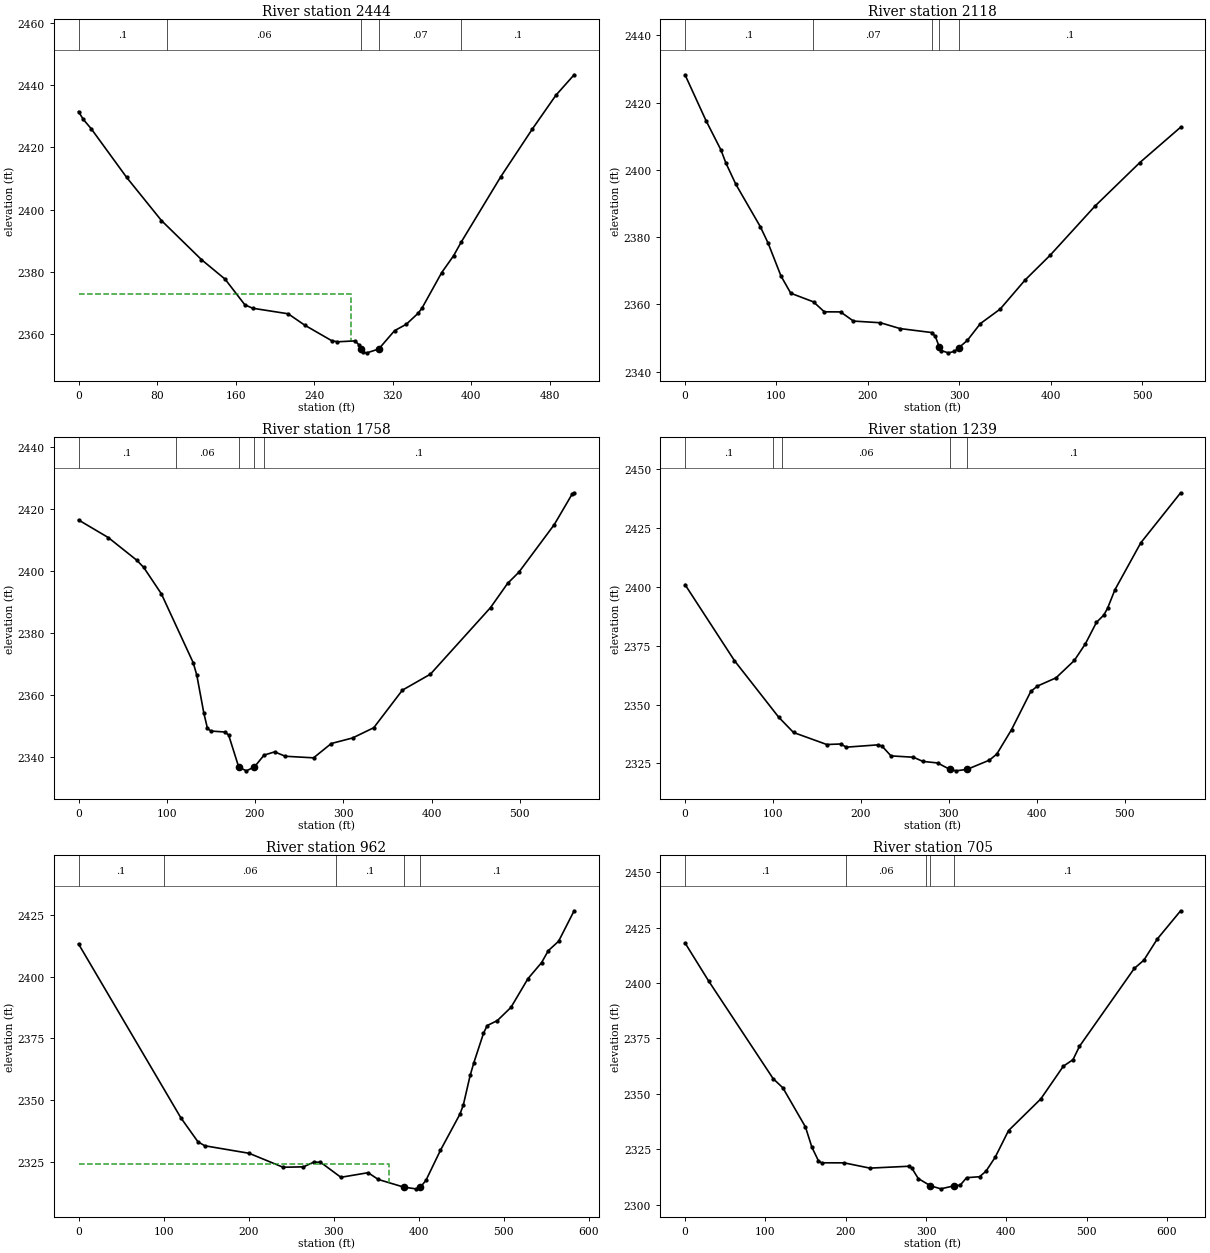
Type RM Length L Ch R = 1 ,2444    ,330.7,325.5,317.4
XS GIS Cut Line= 2
2316669.07971491686385.6388488752316165.73303214686426.768344355
#Sta/Elev= 30
       0 2431.51     4.9 2428.99    12.9 2426.02    49.1 2410.33    84.5 2396.48
   125.3 2383.91   149.4 2377.62   169.5 2369.38   177.5 2368.28   213.6  2366.5
   230.4 2362.86   257.8 2357.88   263.7 2357.49   281.8 2357.78   285.9 2356.45
  287.942355.211   289.9 2354.06   293.9 2353.94   305.9 2355.17     322 2361.06
     334 2363.13   346.1 2366.68   350.1 2368.38   370.1 2379.76   382.2 2385.17
     390 2389.58   430.3 2410.59   462.4  2425.9   486.4 2436.76     505 2443.35
#Mann= 5 ,-1,0
       0      .1       0      90     .06       0  287.94    .045       0
   305.9     .07       0     390      .1       0
#XS Ineff= 2 , 0
          277.26  2372.9
Permanent Ineff=
       F       F
Bank Sta=287.94,305.9
XS Rating Curve= 0 ,0
Exp/Cntr(USF)=0,0
Exp/Cntr=0.3,0.1

Type RM Length L Ch R = 1 ,2118    ,365.6,360.3,351.3
XS GIS Cut Line= 2
2316484.97625896685909.7118297542316087.39113599686277.918741667
#Sta/Elev= 30
       0  2428.3    22.9 2414.69    39.3 2405.92    44.7 2402.04    55.6 2395.69
    82.3 2383.12    90.8 2378.24   104.9 2368.45   115.6 2363.31   140.5 2360.73
   152.3 2357.77     170 2357.75   184.2 2355.02   213.7 2354.52   235.1 2352.79
     270  2351.6   273.7 2350.44  278.142347.238   280.4 2346.24   287.7 2345.57
   294.6 2345.98   299.4  2347.1   308.7 2349.28   322.9 2354.26   344.6 2358.59
   371.8 2367.23   399.3 2374.63   448.1 2389.18   497.2 2402.16   541.9  2412.7
#Mann= 5 ,-1,0
       0      .1       0     140     .07       0     270      .1       0
  278.14    .045       0   299.4      .1       0
Bank Sta=278.14,299.4
XS Rating Curve= 0 ,0
Exp/Cntr(USF)=0,0
Exp/Cntr=0.3,0.1

Type RM Length L Ch R = 1 ,1758    ,507.4,519.1,530.2
XS GIS Cut Line= 2
 2315989.4637658685731.4840160092315950.29281772686291.628573493
#Sta/Elev= 30
       0 2416.51    33.8 2410.82    65.9 2403.55    73.9  2401.2    93.9 2392.68
     130 2370.45     134 2366.49     142 2354.23   146.1 2349.29   150.1 2348.46
   166.1 2348.14   170.1 2347.16   181.5 2336.86   190.2 2335.63  199.332336.898
   210.2  2340.7   222.2 2341.74   234.3 2340.33   266.3 2339.82   286.4 2344.44
   310.5 2346.23   334.5 2349.53   366.9 2361.63   398.7  2366.8   466.8 2388.26
   486.2 2396.08   498.9 2399.66     539 2415.01   559.1 2424.78   561.5 2425.27
#Mann= 5 ,-1,0
       0      .1       0     110     .06       0   181.5    .045       0
  199.33     .06       0     210      .1       0
Bank Sta=181.5,199.33
XS Rating Curve= 0 ,0
Exp/Cntr(USF)=0,0
Exp/Cntr=0.3,0.1

Type RM Length L Ch R = 1 ,1239    ,273.9,277.1,280.3
XS GIS Cut Line= 2
 2315885.6607534685612.0126243772315349.01876476685784.364795911
#Sta/Elev= 30
       0 2401.03    56.2 2368.69   106.6 2344.59   123.4 2338.12   161.2 2333.01
     177 2333.23   183.4 2331.88     220 2332.88   224.2 2332.27   234.2 2328.17
   259.7  2327.6   270.4 2325.83   287.2 2325.16     301 2322.46   308.3 2321.81
   320.9 2322.45   346.1 2326.35   354.5 2328.92   371.3 2339.32   393.2 2355.57
   400.7 2357.86   421.9 2361.37   442.7 2368.75   455.3 2375.85   467.9 2384.99
   476.3 2388.09   480.5 2390.97   488.9 2398.85   518.3 2418.81   563.6 2440.09
#Mann= 5 ,-1,0
       0      .1       0     100     .07       0     110     .06       0
     301    .045       0   320.9      .1       0
Bank Sta=301,320.9
XS Rating Curve= 0 ,0
Exp/Cntr(USF)=0,0
Exp/Cntr=0.3,0.1

Type RM Length L Ch R = 1 ,962     ,259.5,256.6,253.2
XS GIS Cut Line= 3
2315891.53639561685433.7848106322315760.31371955685451.411737266
2315309.84781668685443.577547651
#Sta/Elev= 30
       0 2413.22   120.4 2342.87   140.5 2333.18   148.5 2331.58   200.6 2328.54
   240.6 2322.89   264.6 2323.06   276.6 2324.94   284.6 2324.93   308.6 2318.83
   340.6 2320.69   352.6 2317.95   382.5 2314.86   396.6 2314.16   402.1 2314.85
   408.6 2317.58   425.7 2329.76   448.6 2344.37   452.6 2348.09   460.6 2360.01
     465  2365.2   476.3 2377.05   480.6 2380.19   492.6 2382.21   508.6 2387.55
   528.6 2399.16   544.6 2405.65   552.6 2410.52   564.6 2414.27   582.9 2426.62
#Mann= 5 ,-1,0
       0      .1       0     100     .06       0   302.4      .1       0
   382.5    .045       0   402.1      .1       0
#XS Ineff= 2 , 0
          364.75 2324.11
Permanent Ineff=
       F       F
Bank Sta=382.5,402.1
XS Rating Curve= 0 ,0
Exp/Cntr(USF)=0,0
Exp/Cntr=0.3,0.1

Type RM Length L Ch R = 1 ,705     ,411.8,401,384
XS GIS Cut Line= 2
 2315889.5778482685183.0907429472315274.59396341685232.054428042
#Sta/Elev= 30
       0  2418.1    29.5 2400.86   109.7 2356.84   121.8  2352.7   149.9 2335.05
   157.9 2325.91   165.9  2319.9   169.9 2318.87     198 2318.85   230.1 2316.47
   278.3 2317.31   282.3 2316.49   290.3 2311.77  305.462308.502   318.4 2307.12
     335  2308.5   342.5 2308.76   350.5 2312.16   366.6 2312.58   374.6 2315.07
   386.1  2321.4   402.7 2333.42   442.8 2347.68   470.9 2362.47   482.9 2365.41
     491 2371.45   559.2 2406.58   571.2 2410.35   587.8 2419.85   616.9 2432.61
#Mann= 5 ,-1,0
       0      .1       0     200     .06       0     300      .1       0
  305.46    .045       0     335      .1       0
Bank Sta=305.46,335
XS Rating Curve= 0 ,0
Exp/Cntr(USF)=0,0
Exp/Cntr=0.3,0.1

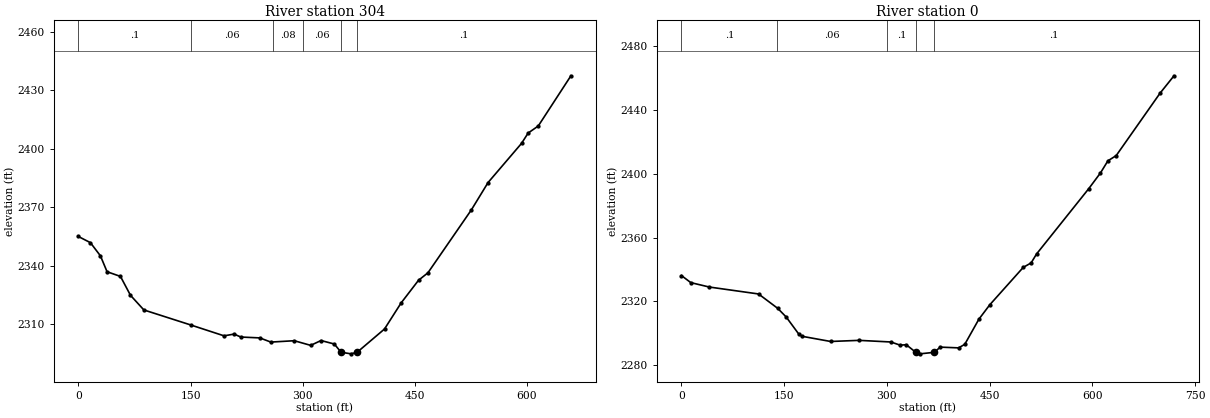
Type RM Length L Ch R = 1 ,304     ,317,304.4,292.9
XS GIS Cut Line= 2
2315535.08076812684630.7803750782315241.29865755685220.303143619
#Sta/Elev= 30
       0 2354.97    16.1 2351.81    29.5 2345.05    38.4 2336.88    56.3 2334.49
    69.7  2324.8    87.6 2317.28     150 2309.61   194.8    2304   208.3 2304.89
   217.2 2303.38   242.6 2302.94   257.4 2300.79   288.7 2301.49   310.7 2299.11
   324.5 2301.59   342.3  2299.8   351.3 2295.58   364.7 2294.76     373 2295.63
   409.4  2307.5   431.7 2320.92   454.9 2332.51   467.5 2336.35   525.6 2368.65
   547.9 2382.66   592.6 2402.72   601.5 2408.05     615 2411.66   658.7 2437.43
#Mann= 6 ,-1,0
       0      .1       0     150     .06       0     260     .08       0
     300     .06       0   351.3    .045       0     373      .1       0
Bank Sta=351.3,373
XS Rating Curve= 0 ,0
Exp/Cntr(USF)=0,0
Exp/Cntr=0.3,0.1

Type RM Length L Ch R = 1 ,0       ,459.5,462.9,464.8
XS GIS Cut Line= 3
2314947.15996427684589.0053514392315138.22379906684961.947259739
2315118.01512423685261.403077734
#Sta/Elev= 30
       0 2336.25    13.7 2331.82    40.6 2329.06   112.6 2324.71   140.6 2315.69
     153 2310.25     171 2299.76   176.2 2298.17   217.8 2294.93   259.4 2295.63
   305.8 2294.61   319.3 2292.63   328.3 2292.88  342.152288.149   348.3 2287.18
   369.4 2288.14   377.7 2291.39   404.7 2290.92   413.7 2293.14   434.3 2308.89
   450.3 2317.97   499.1 2341.38   510.6 2344.19   518.5 2349.77   594.7 2390.71
   611.8 2400.56   622.7 2408.17   634.8 2411.45   698.9 2450.61   719.2 2461.48
#Mann= 5 ,-1,0
       0      .1       0     140     .06       0     300      .1       0
  342.15    .045       0   369.4      .1       0
Bank Sta=342.15,369.4
XS Rating Curve= 0 ,0
Exp/Cntr=0.3,0.1
LCMann Table=0

Chan Stop Cuts=-1
Use User Specified Reach Order=0
Composite Channel Slope=5